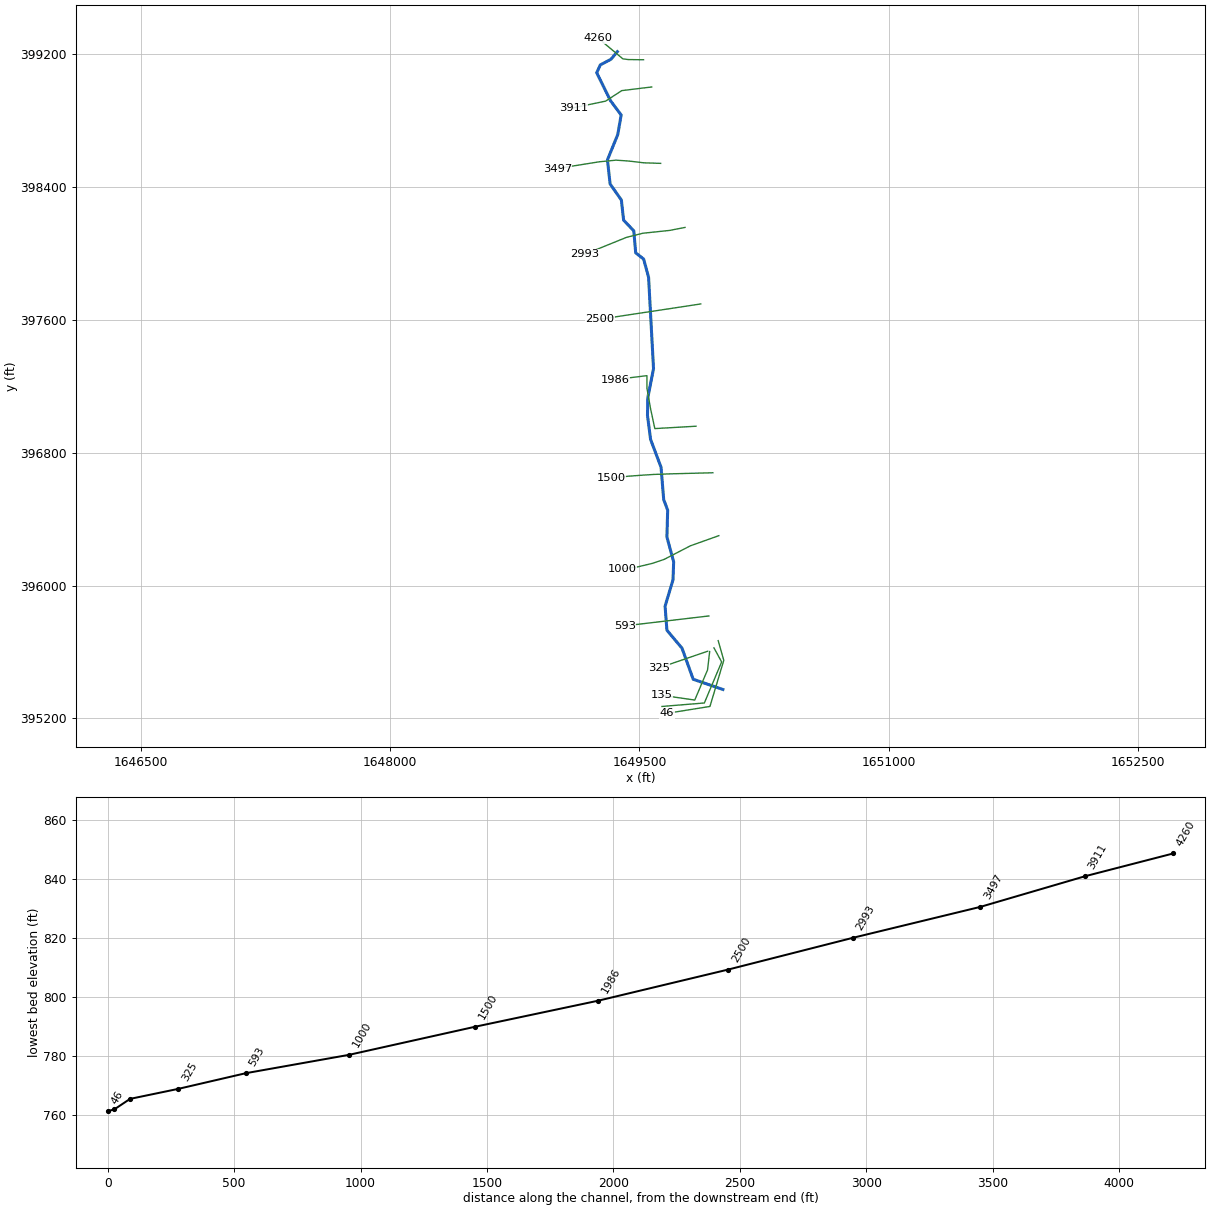
--- MAUDRN.prj (project) ---

Proj Title=MAUDRN
Current Plan=p01
Default Exp/Contr=0,0
English Units
Geom File=g01
Flow File=f01
Plan File=p01
BEGIN DESCRIPTION:
---------- MODELED AS PART OF WVEMD CTP PROGRAM, 2023----------
Stream Name: Maud Run
Flood Zone:  AFH
Wetzel County, WV
HEC-RAS Version: RAS 6.3
Vertical Datum: NAVD88
Projection: NAD 1983 StatePlane West Virginia S FIPS 4702 (US Feet)
Terrain: 1-meter West Virginia FEMA R3 South Central (collected 2018-2020)
Land Use: 2019 NLCD
Hydrologic Method:
WV 2010 Regional Regression Equations
Additional Model Notes:
None
END DESCRIPTION:
DSS Export Rating Curves= 0
DSS Export Rating Curve Sorted= 0
DSS Export Volume Flow Curves= 0
DXF OffsetX= 0
DXF OffsetY= 0
DXF ScaleX= 0
DXF ScaleY= 0

--- MAUDRN.p01 (plan) ---

Plan Title=Floodplain
Program Version=6.30
Short Identifier=Floodplain
Geom File=g01
Flow File=f01
Subcritical Flow
K Sum by GR= 0
Std Step Tol= 0.01
Critical Tol= 0.01
Num of Std Step Trials= 20
Max Error Tol= 0.3
Flow Tol Ratio= 0.001
Split Flow NTrial= 30
Split Flow Tol= 0.02
Split Flow Ratio= 0.02
Log Output Level= 0
Friction Slope Method= 1
Unsteady Friction Slope Method= 2
Unsteady Bridges Friction Slope Method= 1
Parabolic Critical Depth
Global Vel Dist= 0 , 0 , 0
Global Log Level= 0
CheckData=False
Encroach Param=-1 ,0,0, 0
Mapping Interval=1HOUR
Computation Time Step Use Courant=        0
Computation Time Step Use Time Series=    0
Computation Time Step Count To Double=0
Computation Time Step Max Doubling=0
Computation Time Step Max Halving=0
Computation Time Step Residence Courant=0
Run HTab= 0
Run UNet= 0
Run Sediment= 0
Run PostProcess= 0
Run WQNet= 0
Run RASMapper=-1
UNET Theta= 0
UNET Theta Warmup= 0
UNET ZTol= 0
UNET ZSATol= 0
UNET MxIter= 0
UNET Max Iter WO Improvement= 0
UNET MaxInSteps= 0
UNET DtIC= 0
UNET DtMin= 0
UNET MaxCRTS= 0
UNET WFStab= 0
UNET SFStab= 0
UNET WFX= 1
UNET SFX= 1
UNET Gravity=32.17405
UNET 1D Methodology=Finite Difference
UNET DSS MLevel= 1
UNET Pardiso=0
UNET DZMax Abort= 0
UNET Use Existing IB Tables= 0
UNET Froude Reduction=False
UNET Froude Limit= 0
UNET Froude Power= 0
UNET D1 Cores= 0
UNET WindReference=Eulerian
UNET WindDragFormulation=Hsu (1988)
UNET D2 Coriolis=0
UNET D2 Cores= 0
UNET D2 Theta= 1
UNET D2 Theta Warmup= 1
UNET D2 Z Tol= 0.01
UNET D2 Volume Tol= 0.01
UNET D2 Max Iterations= 20
UNET D2 Equation= 0
UNET D2 RampUpFraction=0.1
UNET D2 TimeSlices= 1
UNET D2 Turbulence Formulation=Non-Conservative (original)
UNET D2 Eddy Viscosity=0.3
UNET D2 Transverse Eddy Viscosity=0.1
UNET D2 Smagorinsky Mixing=0
UNET D2 BCVolumeCheck=0
UNET D2 Cores=0
UNET D2 SolverType=PARDISO (Direct)
UNET D2 Minimum Iterations= 3
UNET D2 Maximum Iterations= 30
UNET D2 Restart Number= 10
UNET D2 Relaxation Coeff=1.3
UNET D2 SOR Precondition Iterations= 10
UNET D2 ILUT Maximum Fill= 8
UNET D2 ILUT Tolerance=1E-08
UNET D2 Convergence Tolerance=0.00001
UNET D1D2 MaxIter= 0
UNET D1D2 ZTol=0.01
UNET D1D2 QTol=0.1
UNET D1D2 MinQTol=1
Write IC File= 0
Write IC File at Fixed DateTime=0
Write IC File at Sim End=0
Echo Input=False
Echo Parameters=False
Echo Output=False
Write Detailed= 0
HDF Write Warmup=0
HDF Write Time Slices=0
HDF Flush=0
HDF Compression= 1
HDF Chunk Size= 1
HDF Spatial Parts= 1
HDF Use Max Rows=0
HDF Fixed Rows= 1
Calibration Method= 0
Calibration Iterations= 20
Calibration Max Change=0.05
Calibration Tolerance=0.2
Calibration Maximum=1.5
Calibration Minimum=0.5
Calibration Optimization Method= 1
WQ AD Non Conservative
WQ ULTIMATE=-1
WQ Max Comp Step=1HOUR
WQ Output Interval=15MIN
WQ Output Selected Increments= 0
WQ Output face flow=0
WQ Output face velocity=0
WQ Output face area=0
WQ Output face dispersion=0
WQ Output cell volume=0
WQ Output cell surface area=0
WQ Output cell continuity=0
WQ Output cumulative cell continuity=0
WQ Output face conc=0
WQ Output face dconc_dx=0
WQ Output face courant=0
WQ Output face peclet=0
WQ Output face adv mass=0
WQ Output face disp mass=0
WQ Output cell mass=0
WQ Output cell source sink temp=0
WQ Output nsm pathways=0
WQ Output nsm derived pathways=0
WQ Create Restart=0
WQ Fixed Restart=0
WQ System Summary=0
WQ Write To DSS=0
Sorting and Armoring Iterations= 10
XS Update Threshold= 0.02
Bed Roughness Predictor= 0
Hydraulics Update Threshold= 0.02
Energy Slope Method= 1
Volume Change Method= 1
Sediment Retention Method= 0
Sediment TS Multiplier= 1
Warm Up Method= 0
XS Weighting Method= 0
Number of US Weighted Cross Sections= 1
Number of DS Weighted Cross Sections= 1
Upstream XS Weight=0
Main XS Weight=1
Downstream XS Weight=0
Number of DS XS's Weighted with US Boundary= 1
Upstream Boundary Weight= 1
Weight of XSs Associated with US Boundary= 0
Number of US XS's Weighted with DS Boundary= 1
Downstream Boundary Weight= 0.5
Weight of XSs Associated with DS Boundary= 0.5
Percentile Method= 0
Sediment Output Level= 3
Mass or Volume Output= 0
Output Increment Type= 1
Profile and TS Output Increment= 1
Transport Output Increment 1
XS Output Flag= 0
XS Output Increment= 10
Read HDF5 Sediment Hotstart= 0
Sediment Hotstart Type= 0
Write Gradation File= 0
Read Gradation Hotstart= 0
Write HDF5 File= 1
Write Binary Output= 1
Write DSS Sediment File= 0
DSS Sediment Output Type= 1
SV Curve= 0
Specific Gage Flag= 0
Subcell Erosion Methods= 0
Subcell Deposition Methods= 0
Advection Scheme= 1
Matrix Solver= 0
Implicit Weighting Factor= 1
Maximum Outer Loop Convergence Iterations= 5
Convergence Maximum Absolute= 0.001
Convergence RMSE= 0.0001
Grain Fractions Max Abs Error= 0.001
Max Subgrid Regions= 1
Max Subgrid Length Scale= 3.402823E+38
Initial Layer Thickness= 3.402823E+38
Min Layer Thickness= 3.402823E+38
Max Layer Thickness= 3.402823E+38
Number of Layers= 5

--- MAUDRN.f01 (steady flow) ---

Flow Title=Flow
Program Version=6.31
Number of Profiles= 1
Profile Names=F01pct
River Rch & RM=MAUDRN,Main,4260
     656
Boundary for River Rch & Prof#=MAUDRN,Main            , 1
Up Type= 0
Dn Type= 3
Dn Slope=0.02718
DSS Import GetInterval= 0
DSS Import GetPeak= 0
DSS Import FillOption= 0

--- MAUDRN.g01 (geometry) ---

Geom Title=Geometry
Program Version=6.30

River Reach=MAUDRN          ,Main
Reach XY= 30
 1649367.5569298399212.9455213811649328.25266972399166.735501373
1649264.88770869399133.5538498581649243.16312739399085.973796887
     1649326.158      398917.794     1649390.185      398831.963
     1649370.112       398715.33     1649307.815      398561.319
     1649323.736      398416.652      1649391.57      398319.746
     1649405.067      398198.614     1649466.326      398134.587
     1649477.747       398002.38     1649525.507      397964.655
     1649555.271      397855.291     1649585.035      397305.004
     1649550.772      397131.265     1649548.696       397023.63
     1649567.384      396878.964     1649630.373      396711.801
     1649646.293      396516.951     1649670.174      396453.617
     1649665.675      396291.992     1649706.168       396142.48
     1649702.361      396034.499       1649654.6      395875.642
     1649665.675      395730.976     1649756.351      395622.995
     1649823.839      395435.7591650002.49797418395374.372848597

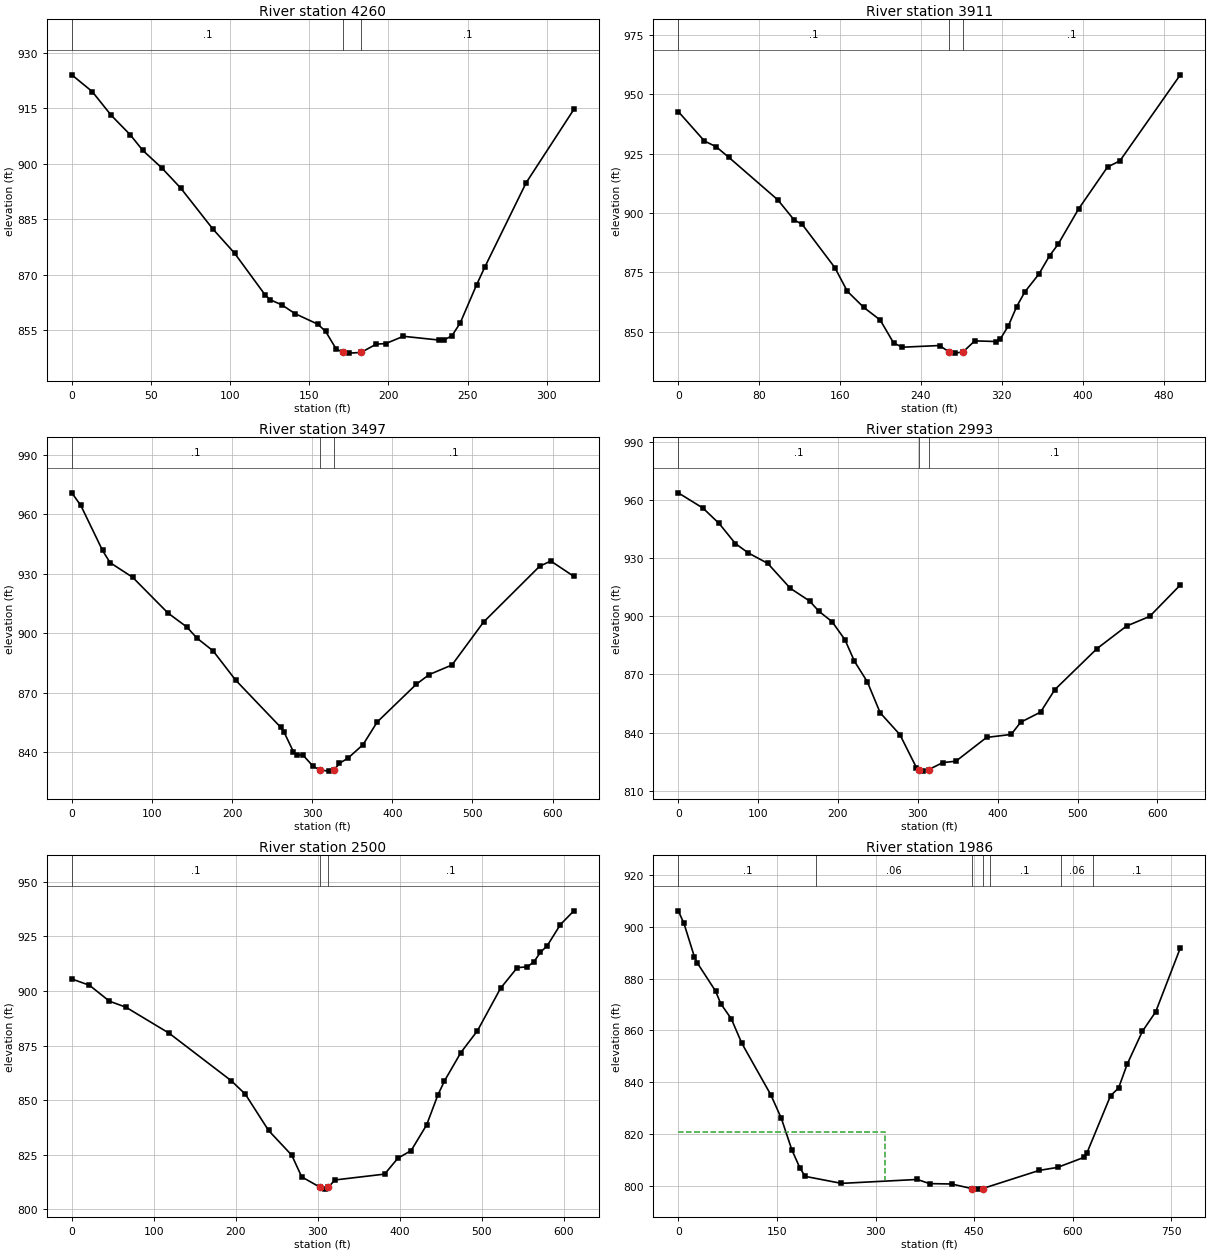
Type RM Length L Ch R = 1 ,4260    ,343.8,349.3,359.4
XS GIS Cut Line= 4
1649525.01674735399164.174211051 1649431.5128967399165.506807498
1649400.49108372 399169.804034661649253.03413812 399293.19259451
#Sta/Elev= 30
       0  924.01    12.9  919.49    24.9  913.07    36.9  907.81    44.9  903.56
    56.9  898.82    68.9  893.34    88.9  882.43   102.8  875.79   122.1  864.51
   125.3   863.2   132.7   861.8     141  859.44   155.4  856.58   160.3  854.65
     167  849.87  171.54  848.94   175.3  848.76   182.7  848.94   192.3  851.19
   198.3  851.34   209.4  853.31   232.1  852.29   235.1  852.32   240.1  853.45
   245.3  856.88   255.7  867.25   260.9  872.06     287  894.84317.1028  914.66
#Mann= 3 ,-1,0
       0      .1       0  171.54    .045       0   182.7      .1       0
Bank Sta=171.54,182.7
XS Rating Curve= 0 ,0
Exp/Cntr(USF)=0,0
Exp/Cntr=0.3,0.1

Type RM Length L Ch R = 1 ,3911    ,413,413.8,407
XS GIS Cut Line= 4
1649573.87329387399000.3898550381649393.98747579398978.614203375
1649296.47042704398915.1807833141649101.61621535398874.706474245
#Sta/Elev= 30
       0   942.7    25.9  930.28    37.4   927.9    50.1  923.39    98.5   905.5
   114.6  897.07   122.6   895.2   154.9  876.98   167.2  867.05   183.4  860.28
   199.7  854.95     213  845.28   221.6   843.5   258.4  844.21   267.9  841.51
   273.7  841.01   281.6 841.508   293.2  846.16   314.2   845.9   318.3  846.82
   326.5  852.52   334.7  860.61   342.8  866.81   356.5  874.18   367.3  882.07
   375.5  886.73   395.9  901.69   424.5  919.33   436.8  921.95   496.5  958.14
#Mann= 3 ,-1,0
       0      .1       0   267.9    .045       0   281.6      .1       0
Bank Sta=267.9,281.6
XS Rating Curve= 0 ,0
Exp/Cntr(USF)=0,0
Exp/Cntr=0.3,0.1

Type RM Length L Ch R = 1 ,3497    ,500.1,504,503.7
XS GIS Cut Line= 6
1649627.92502151398540.6723768411649526.76675926398544.008656248
 1649437.2564396398554.5949211721649359.96197475 398559.98204951
1649258.95495893398550.222226501 1649005.9223285398509.741992503
#Sta/Elev= 30
       0  970.77    11.3   964.4    38.4  941.74    47.8  935.61    75.9  928.25
     120  910.25   143.7  903.16   156.2   897.6   176.4  891.16   204.5  876.43
   260.7  852.71   264.7  850.43   276.7  840.31   280.7  838.91   288.8  838.57
   300.8  833.21   309.3   831.2   320.9   830.6   327.4831.2016   334.1  834.53
   344.9  837.21   363.5  843.93   381.2  855.35   430.1  874.41   446.1  879.23
   474.5  884.06   513.9  905.66   583.8  933.74   597.8  936.43   626.6  928.68
#Mann= 3 ,-1,0
       0      .1       0   309.3    .045       0   327.4      .1       0
Bank Sta=309.3,327.4
XS Rating Curve= 0 ,0
Exp/Cntr(USF)=0,0
Exp/Cntr=0.3,0.1

Type RM Length L Ch R = 1 ,2993    ,492.3,492.8,491
XS GIS Cut Line= 6
1649774.40963668398155.1596964151649682.14801018398137.217475086
1649520.59419942398120.1200683411649422.86407992 398095.54301776
 1649262.1501625398030.4834365841649170.87967576397994.431999505
#Sta/Elev= 30
       0  963.63    30.9  955.77    51.2  947.82    71.6  937.43    87.9  932.59
   112.1  927.23   140.3   914.4   164.4  907.86   176.4  902.45   192.6  897.19
   208.7  887.91   220.7  876.72   236.8  866.15   252.9  850.15   277.6   838.9
   298.2  821.94   300.9820.9093   306.4  820.09   313.8 820.898   331.2  824.48
   347.7  825.21   386.1  837.47   416.9  839.01   428.8  845.31   453.7  850.53
   471.6  862.14   524.4  883.29   561.4  894.92   590.3  899.88   628.7   916.1
#Mann= 3 ,-1,0
       0      .1       0   300.9    .045       0   313.8      .1       0
Bank Sta=300.9,313.8
XS Rating Curve= 0 ,0
Exp/Cntr(USF)=0,0
Exp/Cntr=0.3,0.1

Type RM Length L Ch R = 1 ,2500    ,517.7,513.9,498.3
XS GIS Cut Line= 6
1649869.46817359397694.6740688381649616.16684292397656.175786257
1649517.27530843397641.3264065091649443.10255651397630.144998416
 1649356.5754986397617.0406939241649263.87128767397602.974449083
#Sta/Elev= 30
       0  905.44    21.6  902.56    45.9  895.28    66.1  892.52   118.7  880.64
   194.7  858.85   211.8  852.71   240.1  836.13   268.4  824.81   280.5  814.91
   303.1  810.13   308.8  809.31   312.9  810.12     321   813.5   381.7  816.18
   397.8  823.44     414  826.94   432.9  838.68   446.4  852.15   454.5  858.69
   474.7   871.8   494.9  881.76   523.2  901.24   543.5  910.64   555.6  910.97
   563.7  913.24   571.8  917.68   579.9  920.58   596.1  930.31   612.5  936.61
#Mann= 3 ,-1,0
       0      .1       0   303.1    .045       0   312.9      .1       0
Bank Sta=303.1,312.9
XS Rating Curve= 0 ,0
Exp/Cntr(USF)=0,0
Exp/Cntr=0.3,0.1

Type RM Length L Ch R = 1 ,1986    ,483.4,486.7,499.3
XS GIS Cut Line= 6
1649840.67168379396958.6994333731649592.83347808396944.472409067
1649566.69155134397067.0375228471649545.65227437397186.260092337
1649545.44067085397263.0291879221649354.89460697397239.709886513
#Sta/Elev= 30
       0  906.17     8.6  901.39    24.6  888.39    28.6   886.2    56.7  875.21
    64.7  870.31    80.7  864.47    96.7  855.02   140.8  835.12   156.8  826.03
   172.8  813.85   184.9  806.97   192.9  803.66   248.2  800.95   363.5  802.46
   382.1  800.86   415.7  800.71   446.2  798.95   456.5  798.73   462.8 798.952
   548.9  805.96   576.8  807.12   617.1  811.01   621.1  812.49   657.3  834.78
   669.5  837.75   682.5  846.89   705.7  859.64   725.9  867.14   763.4  891.83
#Mann= 7 ,-1,0
       0      .1       0     210     .06       0   446.2    .045       0
   462.8     .06       0  473.57      .1       0   581.4     .06       0
   631.4      .1       0
#XS Ineff= 2 , 0
          314.54  820.66
Permanent Ineff=
       F       F
Bank Sta=446.2,462.8
XS Rating Curve= 0 ,0
Exp/Cntr(USF)=0,0
Exp/Cntr=0.3,0.1

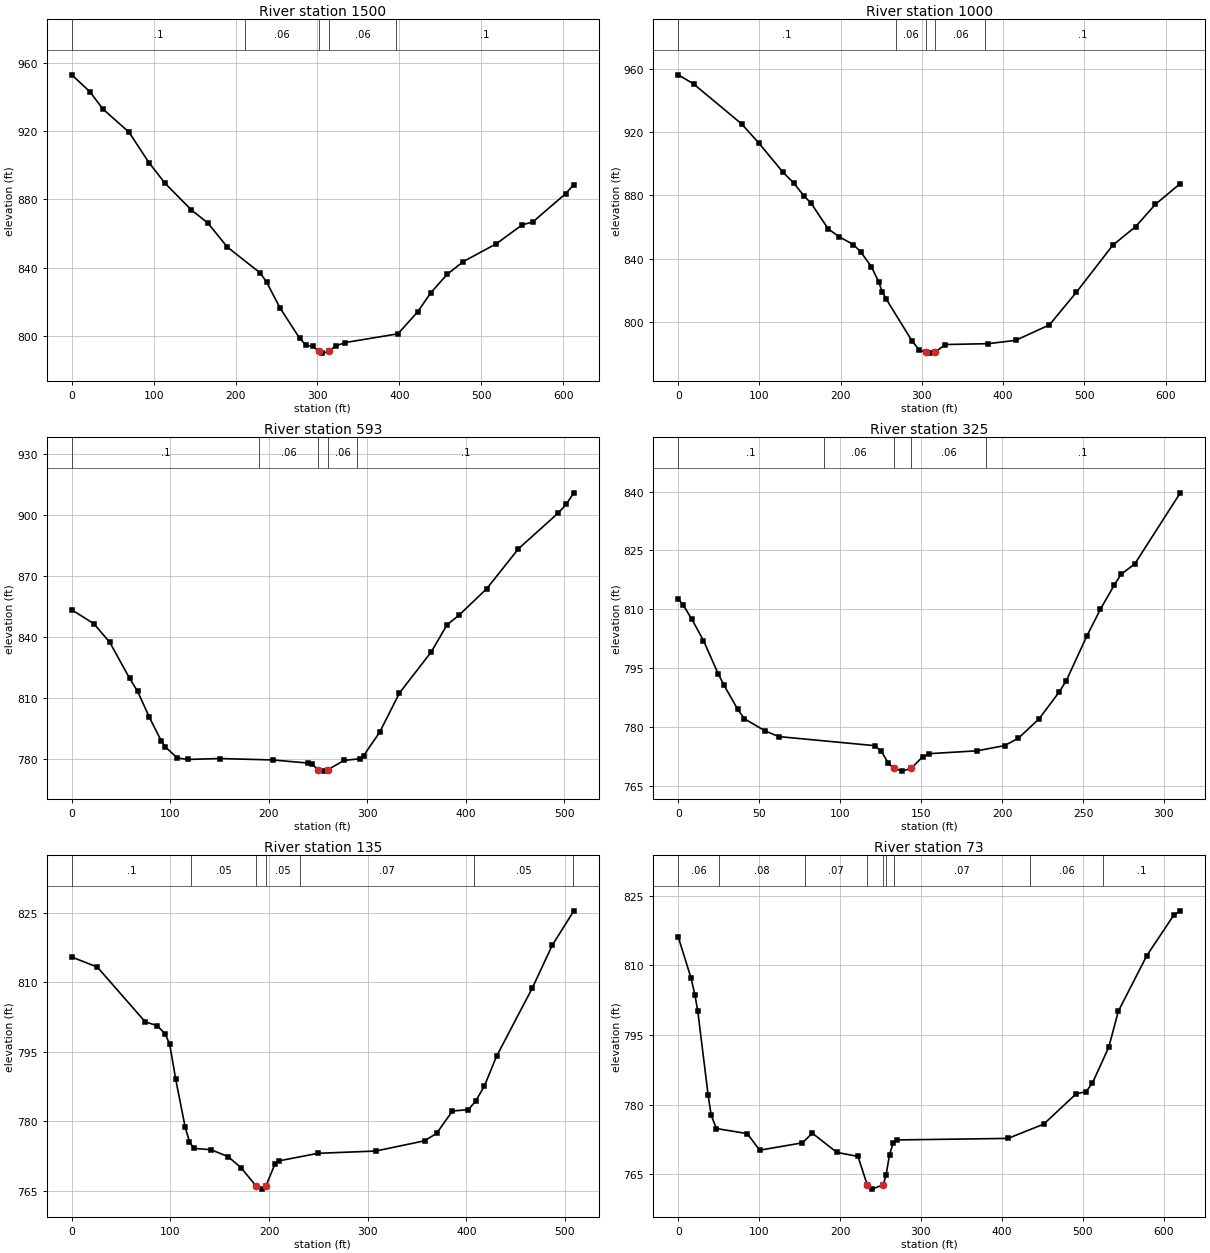
Type RM Length L Ch R = 1 ,1500    ,497.3,499.3,502.6
XS GIS Cut Line= 6
1649942.13600726 396678.63115342  1649685.970181396672.065221667
1649586.02845176396668.5068298431649511.12899525396663.617403924
1649423.77090226396656.9684670871649330.29307084396645.833974928
#Sta/Elev= 30
       0  952.87      22  943.02      38  932.86      70  919.22    94.1  901.52
   114.1  889.26   146.1  873.71   166.1  866.12   190.1  851.93   230.1  836.84
   238.1  831.34   254.1  816.49   278.1   798.7   286.1  794.49   294.1  793.93
   301.9 790.885   306.1  789.88   314.1  790.91   322.1  794.07   334.2  796.09
   398.3  801.19   422.3  814.01   438.3  825.16   458.4  836.03     478  843.45
   518.6  853.98     550  865.01   562.9  866.67   603.2  883.32   613.1  888.59
#Mann= 5 ,-1,0
       0      .1       0  211.25     .06       0   301.9    .045       0
   314.1     .06       0  396.26      .1       0
Bank Sta=301.9,314.1
XS Rating Curve= 0 ,0
Exp/Cntr(USF)=0,0
Exp/Cntr=0.3,0.1

Type RM Length L Ch R = 1 ,1000    ,408.8,407.7,403.2
XS GIS Cut Line= 6
1649977.97058126396299.9626194241649806.16121359396238.659920499
1649650.34295568 396157.790987761649578.63640617396133.407834426
1649492.39215609396112.7799229171649397.66695184 396099.76879409
#Sta/Elev= 30
       0  956.03    18.8  950.32      78  925.06    99.1  913.04   129.1  894.43
   141.9  887.91   154.6  879.66   163.3  875.14   184.7  858.72     198  853.83
   215.6  848.88   224.6  844.28   237.8  834.88   246.7  825.41   251.1  819.08
   255.6  814.81   287.5  788.27   296.6  782.33   304.5780.8937   310.3  780.32
   316.5  780.89   328.6  785.75   381.6  786.29   415.4  788.38     457  798.16
   489.9   818.6   534.9  848.41   563.2  860.26   587.4  874.25   618.1  887.39
#Mann= 5 ,-1,0
       0      .1       0  267.72     .06       0   304.5    .045       0
   316.5     .06       0  378.08      .1       0
Bank Sta=304.5,316.5
XS Rating Curve= 0 ,0
Exp/Cntr(USF)=0,0
Exp/Cntr=0.3,0.1

Type RM Length L Ch R = 1 ,593     ,266.5,267.3,268.1
XS GIS Cut Line= 2
1649918.42255584395816.8744500071649412.31105986395757.263165262
#Sta/Elev= 30
       0  853.28    22.5  846.46    38.6   837.3    58.7  819.65    66.8  813.29
    78.8  800.48    90.9  788.89      95  785.99     107  780.58   117.7  779.82
   150.1  780.28   204.2  779.57     240  778.04     244  777.37   250.2 774.808
   256.1  774.09   260.1   774.8   276.2  779.34   292.3  780.15   296.3  781.76
   312.5  793.18   332.6  812.45   364.8  832.57   380.9  845.95     393  850.63
   421.2  863.68   453.4  883.28   493.7  900.82   501.8  905.05   509.6  910.74
#Mann= 5 ,-1,0
       0      .1       0     190     .06       0   250.2    .045       0
   260.1     .06       0     290      .1       0
Bank Sta=250.2,260.1
XS Rating Curve= 0 ,0
Exp/Cntr(USF)=0,0
Exp/Cntr=0.3,0.1

Type RM Length L Ch R = 1 ,325     ,184.6,190.6,193.5
XS GIS Cut Line= 2
1649910.84810971395604.5530175771649617.46708087395504.032027614
#Sta/Elev= 30
       0  812.67     2.9   811.2     8.5   807.4    15.6  802.03    24.7  793.54
    28.3  790.64    36.7  784.53    40.9  782.09    53.6  779.02    62.1  777.56
   121.3  775.25   125.5  773.81   129.7   770.8   133.1 769.483   138.2  768.76
   143.9  769.47   150.9  772.39   155.1  773.21   184.7  773.94   201.6  775.27
   210.1  777.16   222.8  782.05   235.2  788.87   239.7  791.84   252.4  803.22
   260.8  810.05   269.3  816.19   273.5  818.91     282  821.58   310.1  839.68
#Mann= 5 ,-1,0
       0      .1       0      90     .06       0   133.1    .045       0
   143.9     .06       0     190      .1       0
Bank Sta=133.1,143.9
XS Rating Curve= 0 ,0
Exp/Cntr(USF)=0,0
Exp/Cntr=0.3,0.1

Type RM Length L Ch R = 1 ,135     ,61.9,62,60.2
XS GIS Cut Line= 4
1649922.90536949395602.4927012451649910.07849738395491.860929346
1649833.11726476395310.6813608751649634.30074714395339.541823109
#Sta/Elev= 30
       0  815.46    25.9  813.29    74.5  801.46    86.5  800.66    94.6   798.9
    99.3  796.64   105.3  789.19     115  778.72   119.3  775.61   123.7  774.15
   141.1  773.87   158.4  772.39   171.5  770.01   186.6766.1167   193.2  765.36
     197  766.11   206.2  770.86   210.6  771.48   249.6  773.09   308.2  773.58
   357.7  775.79   369.9  777.39     386  782.22   402.2  782.52   409.6  784.38
   418.4  787.61   430.7  794.03   466.9  808.73   487.2  817.99   509.1  825.43
#Mann= 7 ,-1,0
       0      .1       0  121.37     .05       0   186.6    .045       0
     197     .05       0  231.37     .07       0  408.22     .05       0
  508.22      .1       0
Bank Sta=186.6,197
XS Rating Curve= 0 ,0
Exp/Cntr(USF)=0,0
Exp/Cntr=0.3,0.1

Type RM Length L Ch R = 1 ,73      ,26.5,26.7,26.8
XS GIS Cut Line= 4
 1649948.5591137395624.9397274271649995.05652507395539.961699737
1649890.83818923395293.0444117321649635.90410616395272.200744562
#Sta/Elev= 30
       0  816.11    15.7  807.33    20.6  803.62    24.1  800.19    36.9  782.13
    40.7  777.76    47.1  774.86    85.4  773.76   100.6  770.19   153.6  771.78
   165.7  773.86   196.1  769.72   222.2  768.85   233.7762.6923   239.5  761.81
   253.3762.7174   256.9  764.79   261.2  769.23   265.6  771.69   269.9   772.4
   407.7  772.73   451.9  775.81     492  782.34   504.1  782.78   512.1  784.66
   532.2  792.36   544.2  800.16   579.3  812.09   612.4  820.74   620.7  821.73
#Mann= 9 ,-1,0
       0     .06       0      50     .08       0  156.87     .07       0
   233.7    .045       0   253.3     .07       0  256.87     .05       0
  266.87     .07       0  434.88     .06       0  524.88      .1       0
Bank Sta=233.7,253.3
XS Rating Curve= 0 ,0
Exp/Cntr(USF)=0,0
Exp/Cntr=0.3,0.1

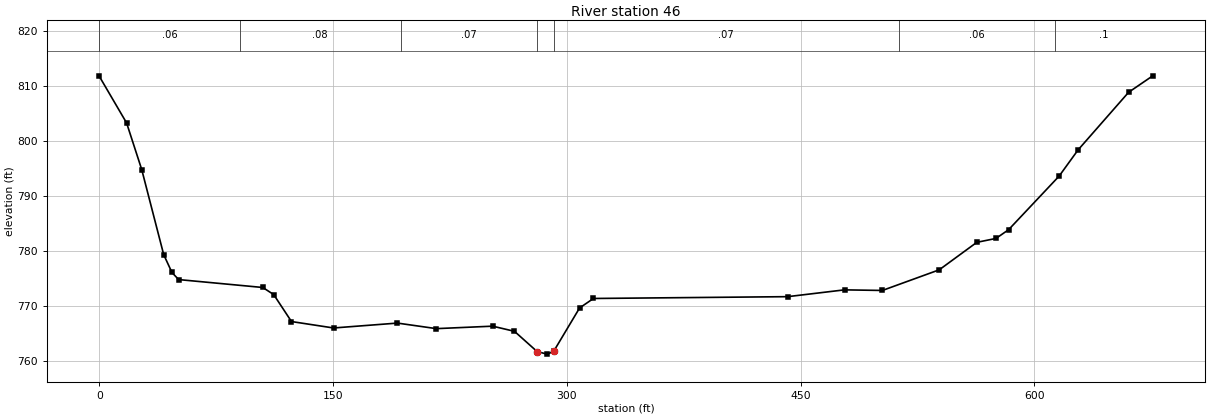
Type RM Length L Ch R = 1 ,46      ,,,
XS GIS Cut Line= 4
 1649974.2128579395668.2304207791650007.88339718395549.581853815
 1649924.5087285395272.2007445621649664.76456839395230.513410224
#Sta/Elev= 30
       0  811.72    17.5  803.24    27.2  794.76    41.3  779.27    46.6  776.02
    50.9  774.73   104.9  773.29   111.9     772   123.3  767.09   150.3  765.92
   191.3  766.81   216.3   765.8   252.4  766.25   266.4  765.31   280.9 761.635
   287.3  761.16   291.5  761.64   308.2  769.57   317.1  771.29   441.7  771.62
   478.2  772.86   502.5  772.75     539  776.51   563.1  781.51   575.4  782.22
   583.5  783.81   615.9  793.56   628.1  798.34   660.5  808.82     676  811.82
#Mann= 7 ,-1,0
       0     .06       0      90     .08       0  193.33     .07       0
   280.9    .045       0   291.5     .07       0  512.97     .06       0
  612.97      .1       0
Bank Sta=280.9,291.5
XS Rating Curve= 0 ,0
Exp/Cntr(USF)=0,0
Exp/Cntr=0.3,0.1
LCMann Table=0

Chan Stop Cuts=-1
Use User Specified Reach Order=0
Composite Channel Slope=5